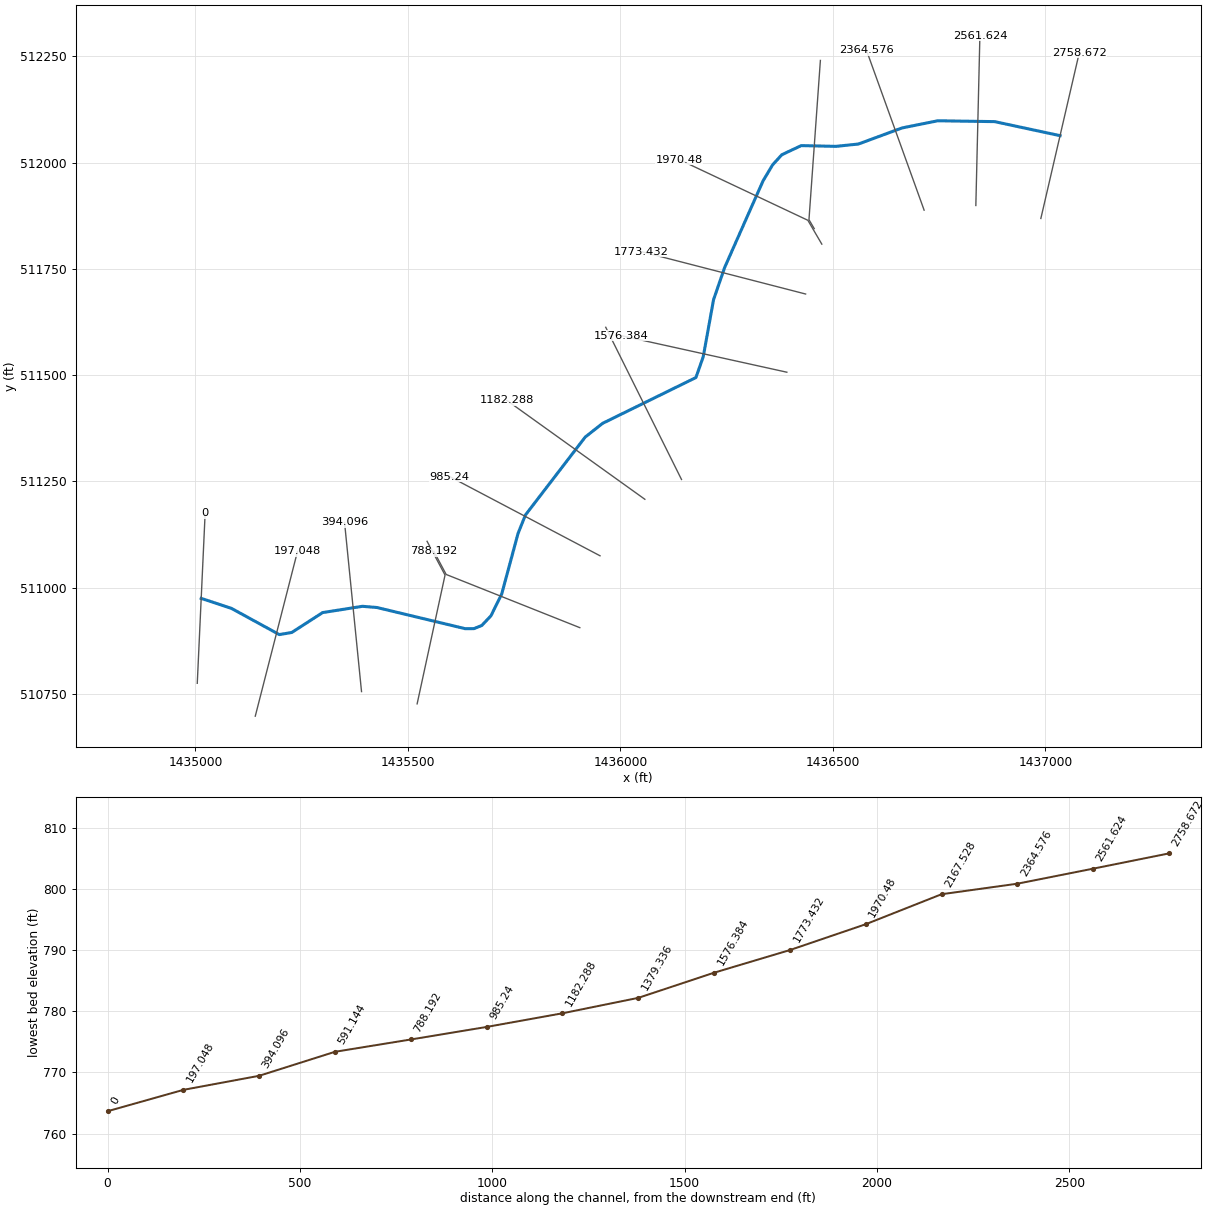
--- 6433Yankee.prj (project) ---

Proj Title=HEC-RAS Model
Current Plan=p01
Default Exp/Contr=0.3,0.1
English Units
Geom File=g01
Flow File=f01
Plan File=p01
Y Axis Title=Elevation
X Axis Title(PF)=Main Channel Distance
X Axis Title(XS)=Station
BEGIN DESCRIPTION:
CRS Info=<SpatialReference>  <CoordinateSystem Code="3754" Unit="US_survey_Foot" AcadCode="" />  <Registration OffsetX="0" OffsetY="0" OffsetZ="0" ScaleX="1" ScaleY="1" ScaleZ="1" /></SpatialReference>
END DESCRIPTION:
DSS Export Rating Curves= 0
DSS Export Rating Curve Sorted= 0
DSS Export Volume Flow Curves= 0
DXF OffsetX= 0
DXF OffsetY= 0
DXF ScaleX= 1
DXF ScaleY= 10

--- 6433Yankee.p01 (plan) ---

Plan Title=Default Scenario
Program Version=6.41
Short Identifier=Default Scenario
BEGIN DESCRIPTION:
Default Scenario
END DESCRIPTION:
Geom File=g01
Flow File=f01
Subcritical Flow
Encroach Param=0,       0,       0,0
Disregard all LS=0
Disregard all Conn=0
Disregard all Breaches=0
Disregard all Pumps=0
Run HTab=1
Run UNet=1
Run PostProcess=1
UNET Froude Reduction=False
UNET Froude Reduction=False
Computation Interval=1MIN
Output Interval=15MIN
Instantaneous Interval=15MIN
Mapping Interval=15MIN
DSS File=dss
Friction Slope Method=1
K Sum by GR=0
Std Step Tol=    0.01
Critical Tol=    0.01
Num of Std Step Trials=20
Max Error Tol=    0.33
Flow Tol Ratio=   0.001
Split Flow NTrial=30
Split Flow Tol=    0.02
Split Flow Ratio=    0.02
Unsteady Friction Slope Method=2
Unsteady Bridges Friction Slope Method=1
UNET Junction Losses=0
UNET Time Slicing=0,       0,5
UNET Convert EG Bridges=0
UNET Use Existing IB Tables=-1
UNET Froude Power=      10
UNET Froude Limit=       1
UNET Theta=       1
UNET Theta Warmup=       1
UNET ZTol=    0.02
UNET ZSATol=    0.02
UNET Max Iter WO Improvement=       0
UNET Pardiso=       0
UNET 1D Methodology=Finite Difference
UNET D1 Cores=       0
UNET MxIter=20
UNET MaxInSteps=20
UNET DtIC=       0
UNET DtMin=       0
UNET MaxCRTS=20
UNET WFStab=       2
UNET SFStab=       1
UNET WFX=     1.0
UNET SFX=     1.0
UNET DSS MLevel=4
UNET DZMax Abort=     100
Parabolic Critical Depth
Global Vel Dist= 1 , 1 , 1
CheckData=True
Global Log Level=0

--- 6433Yankee.f01 (steady flow) ---

Flow Title=Default Steady Flow
Program Version=6.41
Number of Profiles=1
Profile Names=PF# 1
River Rch & RM=Hunts Creek,R1              ,2758.672
860.0
Boundary for River Rch & Prof#=Hunts Creek,R1              ,1
Up Type=3
Up Slope=0.015698
Dn Type=3
Dn Slope=0.014681

--- 6433Yankee.g01 (geometry) ---

Geom Title=Default Geometry
Program Version=6.41
BEGIN GEOM DESCRIPTION:
Default Geometry
END GEOM DESCRIPTION:

River Reach=Hunts Creek     ,R1
Reach XY= 30
1437034.24461912512063.1664651971436880.56575875512096.198334246
1436746.52124111512098.2214162331436662.25775346512081.272964034
1436559.84932276512043.4876377711436507.24962239512038.021936611
1436425.25455205512039.7834097471436379.64296215512018.317553080
1436357.98142537511994.5651937611436335.50055262511956.829832199
1436245.20545854511753.2977576521436219.00080055511677.261291001
1436194.74801701511543.1549748291436177.51026466511494.056965255
1435957.89000959511386.2948955761435916.96944116511353.938480954
1435776.42418292511170.7008461831435758.97632520511127.248150113
1435720.60718529510984.8419406131435695.23958970510933.447313925
1435673.76593673510910.8079330371435655.45550093510903.345148031
1435634.78218393510903.1685838811435426.96098255510953.019722293
1435393.02419862510955.8411923051435299.14054889510941.032626501
1435226.53283727510894.2252035681435197.35181603510889.285522405
1435084.61724172510950.9875349871435013.50358300510974.499864227

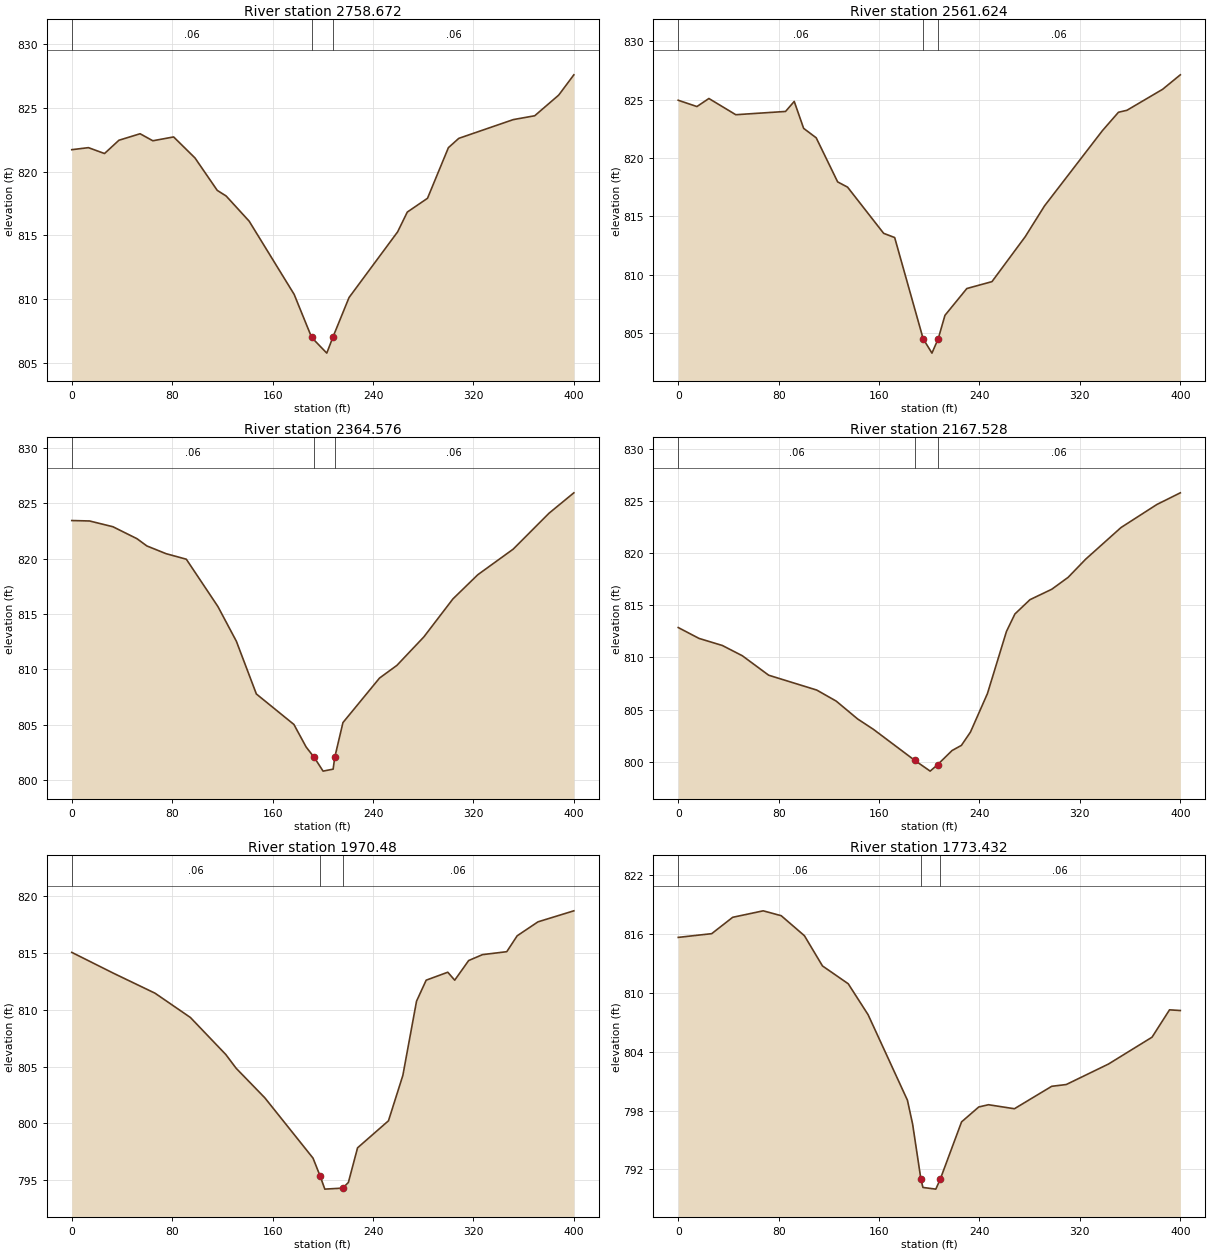
Type RM Length L Ch R = 1 ,2758.672,197.05,197.05,197.05
XS GIS Cut Line= 2
1436989.07260395511868.3345144151437079.41663429512257.998415979
#Sta/Elev= 25
       0  821.72   13.26  821.88   26.09  821.42   37.58  822.46   54.44  822.97
   64.58  822.42   81.17  822.72   98.19  821.07  115.91  818.53  122.99  818.09
   141.3  816.12  177.16  810.38  191.12     807  203.17  805.77  207.95     807
  220.91  810.13  259.62  815.28  267.32  816.83  283.41  817.91  300.07  821.88
  308.35  822.61  351.78  824.08  368.82  824.38  387.94     826     400  827.59
#Mann= 3 , 0 , 0
       0    0.06       0  191.12   0.035       0  207.95    0.06       0
Bank Sta=191.12,207.95
XS Rating Curve= 0 ,0
Exp/Cntr=0.3,0.1

Type RM Length L Ch R = 1 ,2561.624,197.05,197.05,197.05
XS GIS Cut Line= 2
1436836.11975243511898.8705933261436845.66765945512298.756623929
#Sta/Elev= 25
       0  824.96   14.88  824.42   24.43  825.11   45.86  823.72   85.49     824
   92.41  824.86   99.91  822.55  109.92  821.74  127.01  817.96  134.92  817.51
  163.65  813.55  172.43  813.19  195.13  804.51  202.13  803.28  207.11  804.51
   212.5  806.52  229.94  808.82  249.95  809.41  276.43  813.26   291.8   815.9
  337.91  822.35  350.72  823.93  357.48   824.1  385.91   825.9     400  827.14
#Mann= 3 , 0 , 0
       0    0.06       0  195.13   0.035       0  207.11    0.06       0
Bank Sta=195.13,207.11
XS Rating Curve= 0 ,0
Exp/Cntr=0.3,0.1

Type RM Length L Ch R = 1 ,2364.576,197.05,197.05,197.05
XS GIS Cut Line= 2
1436714.42093900511887.8968911401436578.75273670512264.186857633
#Sta/Elev= 25
       0  823.43   14.19  823.39    32.8  822.87   51.98  821.79   59.79  821.14
   75.11  820.44   91.26  819.94  116.43  815.67  131.13  812.54  147.07  807.78
  176.99  805.03  186.75  802.99  193.22802.0500  200.22  800.82  208.24     801
  209.49802.0500  216.05   805.2  245.22  809.22  259.02  810.36  280.51  812.93
  303.68  816.36  323.48  818.54   351.7  820.85  380.13  824.08     400  825.93
#Mann= 3 , 0 , 0
       0    0.06       0  193.22   0.035       0  209.49    0.06       0
Bank Sta=193.22,209.49
XS Rating Curve= 0 ,0
Exp/Cntr=0.3,0.1

Type RM Length L Ch R = 1 ,2167.528,197.05,197.05,197.05
XS GIS Cut Line= 3
1436455.82278832511844.4806778121436443.49475697511865.561783769
1436470.36353263512240.178292857
#Sta/Elev= 25
       0  812.86   16.53  811.82   35.14  811.14   51.03  810.16   72.08  808.29
  110.33  806.87  125.87  805.81  142.91   804.1  155.45  803.11  188.56  800.12
  200.71   799.1  206.56  799.71  218.11  801.07  225.62  801.57   232.8  802.84
   246.3  806.52  261.51  812.49  268.23  814.16  280.22  815.53   297.6  816.53
  310.62  817.67   324.6  819.41  352.72  822.44   381.3  824.65     400  825.77
#Mann= 3 , 0 , 0
       0    0.06       0  188.56   0.035       0  206.56    0.06       0
Bank Sta=188.56,206.56
XS Rating Curve= 0 ,0
Exp/Cntr=0.3,0.1

Type RM Length L Ch R = 1 ,1970.48 ,197.05,197.05,197.05
XS GIS Cut Line= 3
1436473.70578605511807.9576631201436440.90506425 511864.04735596
1436137.91672995512007.011821249
#Sta/Elev= 25
       0  815.06   33.44  813.21   66.37  811.46   94.54  809.32  122.72  806.06
  130.94  804.85  153.85  802.24  192.21  796.93  197.88  795.35   201.6   794.2
  215.88  794.29  220.38  794.79  227.69  797.84  252.31  800.22  263.77  804.22
  274.68  810.76  282.36  812.61  299.56  813.31  305.09  812.61   316.2  814.34
  327.21  814.86  346.56  815.12  354.85  816.52  371.44  817.75     400  818.72
#Mann= 3 , 0 , 0
       0    0.06       0  197.88   0.035       0  215.88    0.06       0
Bank Sta=197.88,215.88
XS Rating Curve= 0 ,0
Exp/Cntr=0.3,0.1

Type RM Length L Ch R = 1 ,1773.432,197.05,197.05,197.05
XS GIS Cut Line= 2
1436435.57847427511690.6026638921436048.26754475511790.553871373
#Sta/Elev= 25
       0  815.66   26.66  816.04    43.4  817.71   67.71  818.37   82.07  817.87
  100.54  815.83  114.91  812.75  135.43  810.93  151.28  807.77   182.6  799.05
  186.74  796.61  193.33     791  194.95  790.15  205.21  789.98  208.77     791
  225.73  796.84  239.42  798.36  247.17  798.59  267.82  798.18  297.56  800.47
  309.14  800.65  342.76  802.74  377.48  805.48   391.4  808.27     400   808.2
#Mann= 3 , 0 , 0
       0    0.06       0  193.33   0.035       0  208.77    0.06       0
Bank Sta=193.33,208.77
XS Rating Curve= 0 ,0
Exp/Cntr=0.3,0.1

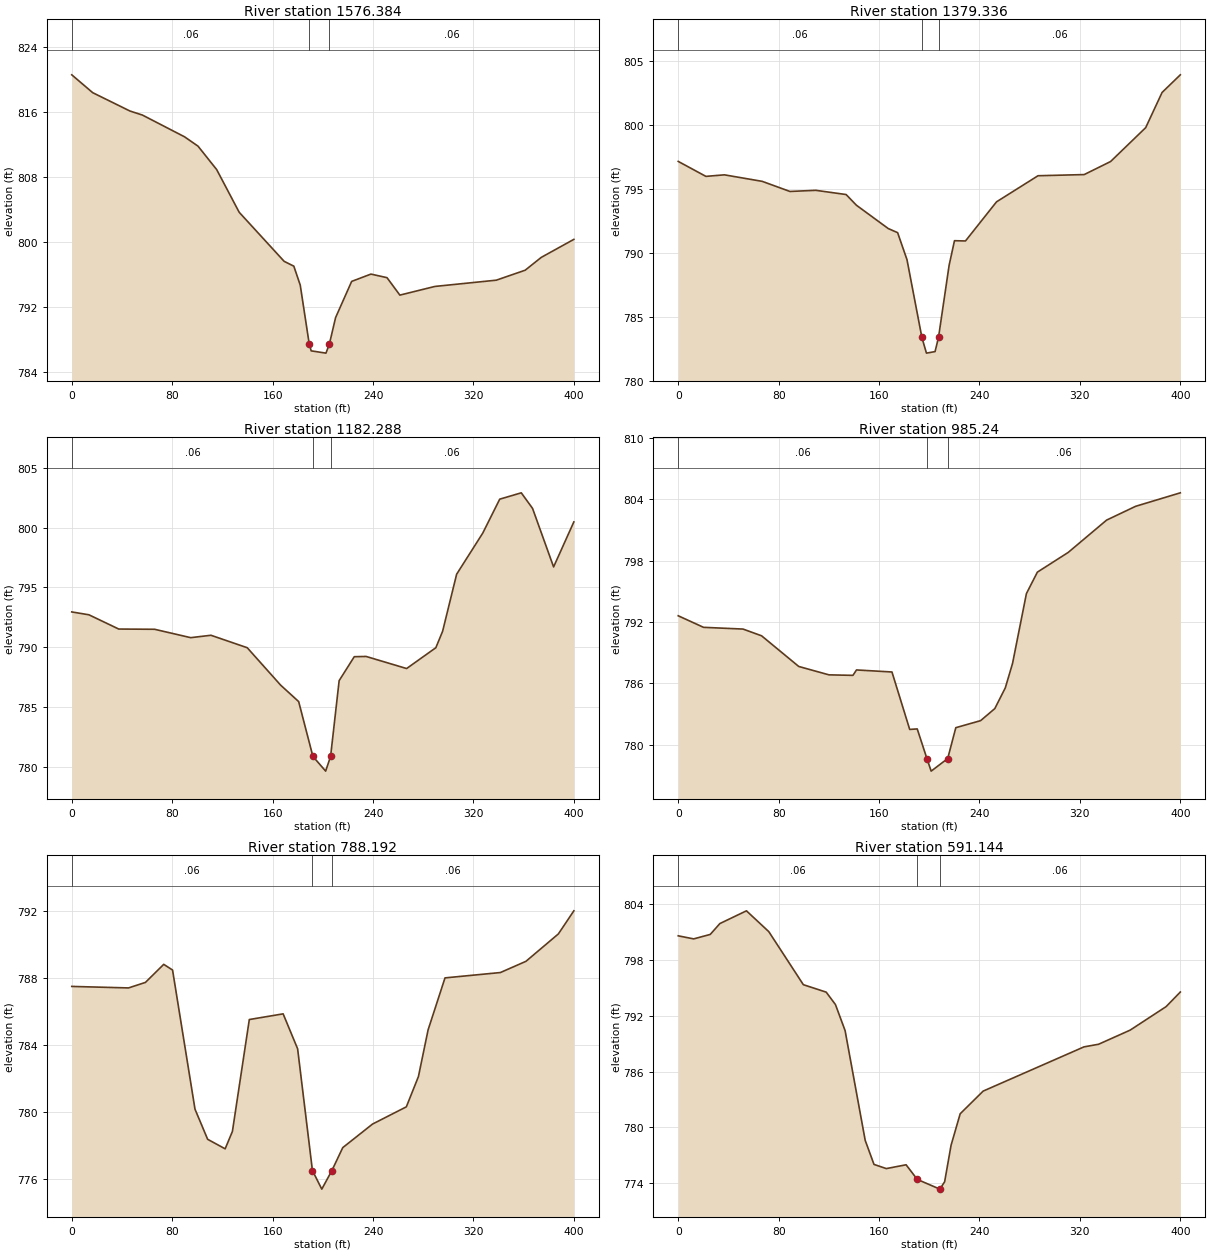
Type RM Length L Ch R = 1 ,1576.384,197.05,197.05,197.05
XS GIS Cut Line= 2
1436391.49683438511506.6151413281436000.89927156511592.833143633
#Sta/Elev= 25
       0  820.58   16.68  818.38   46.34  816.12    56.3  815.62   89.86  812.94
  100.57  811.79  115.46   808.9  133.38  803.64  169.22  797.59  176.91     797
  182.03  794.66   189.2  787.39  190.75  786.56  202.51  786.28  205.22  787.39
  210.19  790.66  222.99  795.12  238.35  796.02  251.15  795.58  261.39  793.43
  289.32   794.5   338.2  795.27  361.24   796.5  374.04  798.08     400   800.3
#Mann= 3 , 0 , 0
       0    0.06       0   189.2   0.035       0  205.22    0.06       0
Bank Sta=189.2,205.22
XS Rating Curve= 0 ,0
Exp/Cntr=0.3,0.1

Type RM Length L Ch R = 1 ,1379.336,197.05,197.05,197.05
XS GIS Cut Line= 2
1436143.57187659511254.2224244461435965.33816402511612.318422336
#Sta/Elev= 25
       0  797.16   22.04  795.99   36.81  796.11   66.93   795.6   89.01  794.81
  109.52   794.9  133.76  794.57  141.89  793.74  167.32  791.91  174.78  791.59
  182.24  789.48  194.11   783.4  197.74  782.17  204.61  782.29  207.36   783.4
   215.8  789.03  220.08  790.96  228.85  790.94  253.59     794  286.65  796.04
  323.41  796.13  344.45  797.15  372.42   799.8  385.47  802.55     400  803.93
#Mann= 3 , 0 , 0
       0    0.06       0  194.11   0.035       0  207.36    0.06       0
Bank Sta=194.11,207.36
XS Rating Curve= 0 ,0
Exp/Cntr=0.3,0.1

Type RM Length L Ch R = 1 ,1182.288,197.05,197.05,197.05
XS GIS Cut Line= 2
1436057.37136599511207.6375729071435732.24589729511440.647078308
#Sta/Elev= 25
       0  792.95   13.68  792.71   37.43  791.52   65.97   791.5   94.77   790.8
  110.89     791  139.79  789.96  166.44  786.83  180.77  785.46  192.11  780.88
  202.27  779.65   206.2  780.88  213.02  787.21  225.08  789.21  234.52  789.23
  266.77  788.22  290.06  789.96  295.44  791.33  306.62   796.1  327.41  799.53
  340.95  802.37  358.12   802.9   367.1   801.6  383.87  796.71     400  800.47
#Mann= 3 , 0 , 0
       0    0.06       0  192.11   0.035       0   206.2    0.06       0
Bank Sta=192.11,206.2
XS Rating Curve= 0 ,0
Exp/Cntr=0.3,0.1

Type RM Length L Ch R = 1 ,985.24  ,197.05,197.05,197.05
XS GIS Cut Line= 2
1435951.90494994511074.6985324701435598.00407209511261.123232170
#Sta/Elev= 25
       0  792.62   20.14  791.49    51.6  791.32   66.41  790.66   96.02  787.66
  120.08  786.84   139.2  786.79  142.02  787.32  170.28  787.12  184.41   781.5
  190.41  781.55  198.12  778.65  201.51  777.42  214.68  778.65  221.14  781.67
  240.92  782.36  252.22  783.54  260.58  785.57  266.35  787.96  277.39  794.79
  286.13  796.89  310.71  798.82  341.27  801.98  364.38  803.33     400  804.65
#Mann= 3 , 0 , 0
       0    0.06       0  198.12   0.035       0  214.68    0.06       0
Bank Sta=198.12,214.68
XS Rating Curve= 0 ,0
Exp/Cntr=0.3,0.1

Type RM Length L Ch R = 1 ,788.192 ,197.05,197.05,197.05
XS GIS Cut Line= 3
1435904.32164429510905.5867332151435589.88343708511030.752439607
1435560.94992138511085.095565199
#Sta/Elev= 25
       0  787.49   45.22   787.4   58.69  787.73   73.27  788.81    80.3  788.47
   98.18  780.15  108.25  778.35   122.2  777.78  127.98  778.82  141.45  785.51
   168.4  785.85  179.94  783.76  191.74  776.48  199.19  775.37  207.24  776.48
  215.88  777.85  239.61  779.26  266.55  780.29  276.18   782.1  283.88  784.89
  297.35     788  341.49  788.32  361.82  788.99  387.69  790.63     400  792.01
#Mann= 3 , 0 , 0
       0    0.06       0  191.74   0.035       0  207.24    0.06       0
Bank Sta=191.74,207.24
XS Rating Curve= 0 ,0
Exp/Cntr=0.3,0.1

Type RM Length L Ch R = 1 ,591.144 ,197.05,197.05,197.05
XS GIS Cut Line= 3
1435521.55117645510726.3273371611435587.23537769511029.342552575
1435544.96350212511108.737876205
#Sta/Elev= 25
       0  800.62    12.3  800.29    25.5  800.77   33.18  801.94   54.34  803.31
   72.15  801.07   99.69  795.36  117.87  794.56  125.27  793.22  132.94  790.42
  148.95  778.61  155.96  776.02  165.77  775.57  181.54  775.98  190.41  774.41
  208.41  773.36  212.24  774.15  217.36  778.08  224.63  781.47  242.94  783.91
  323.28  788.67  334.87  788.95  360.03  790.47  388.68     793     400  794.57
#Mann= 3 , 0 , 0
       0    0.06       0  190.41   0.035       0  208.41    0.06       0
Bank Sta=190.41,208.41
XS Rating Curve= 0 ,0
Exp/Cntr=0.3,0.1

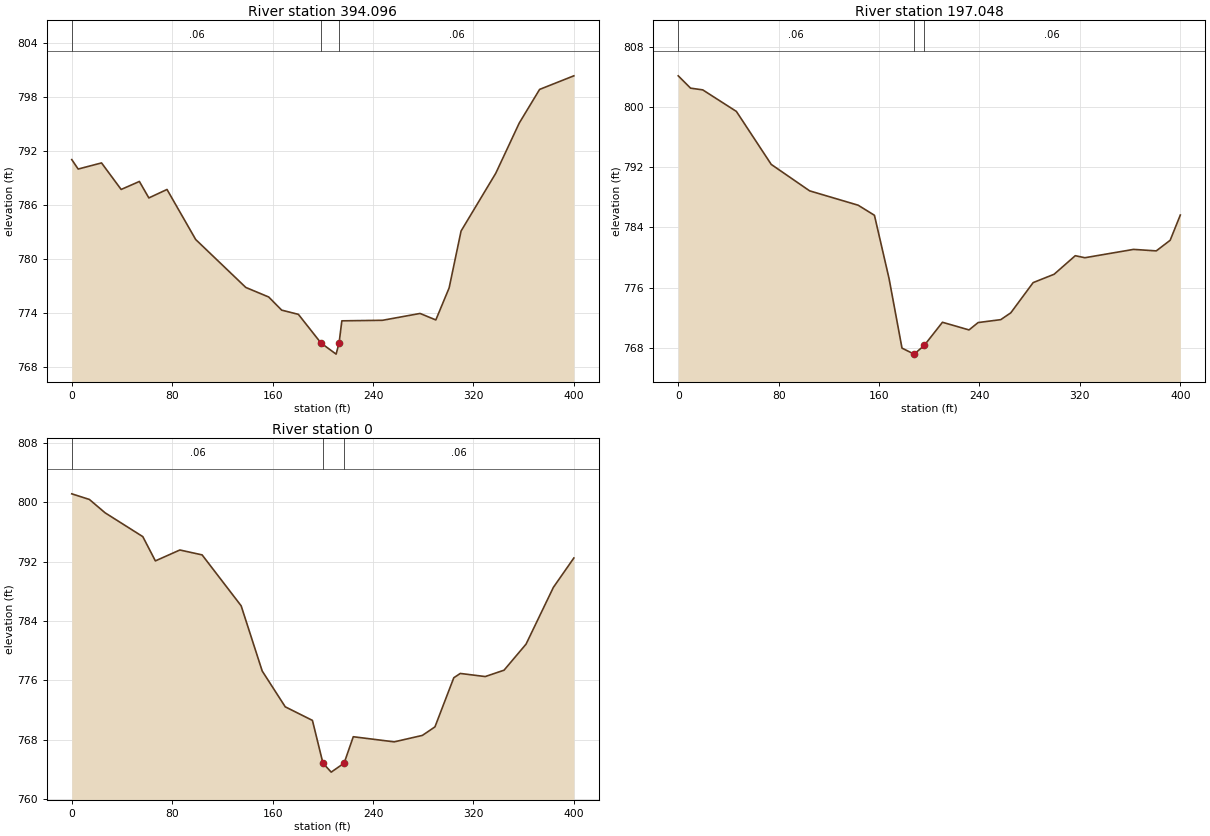
Type RM Length L Ch R = 1 ,394.096 ,197.05,197.05,197.05
XS GIS Cut Line= 2
1435390.73329500510755.1492597441435350.78330942511153.149258051
#Sta/Elev= 25
       0  791.06     5.1  790.01   23.72  790.69   39.35  787.74   53.87  788.63
   61.41   786.8   75.88  787.74   98.72  782.18  138.66  776.85  156.89  775.79
  167.22  774.33  180.55  773.86  198.58770.6700   210.6  769.44  212.95770.6700
  215.17  773.14  247.58   773.2  277.49  773.96  290.05  773.24  300.65   776.8
  310.15  783.12  337.79  789.54  356.51  795.12  372.72  798.86     400  800.37
#Mann= 3 , 0 , 0
       0    0.06       0  198.58   0.035       0  212.95    0.06       0
Bank Sta=198.58,212.95
XS Rating Curve= 0 ,0
Exp/Cntr=0.3,0.1

Type RM Length L Ch R = 1 ,197.048 ,197.05,197.05,197.05
XS GIS Cut Line= 2
1435140.71863598510697.3361953121435240.03304744511084.810901165
#Sta/Elev= 25
       0  804.18    9.82  802.54   19.53  802.31   46.34  799.44    74.1  792.39
  104.69  788.87  143.34  786.96  156.31  785.62  167.99  777.18  178.27  767.94
  187.93  767.14  195.96  768.29  210.51  771.38  231.68  770.36  238.89  771.34
  256.96  771.73  264.97  772.64  282.77  776.66  299.47  777.77  316.32  780.24
  323.96  779.97  362.77  781.08  380.84  780.88  391.91  782.29     400  785.65
#Mann= 3 , 0 , 0
       0    0.06       0  187.93   0.035       0  195.96    0.06       0
Bank Sta=187.93,195.96
XS Rating Curve= 0 ,0
Exp/Cntr=0.3,0.1

Type RM Length L Ch R = 1 ,0       ,0,0,0
XS GIS Cut Line= 2
1435004.24967405510774.7140660111435022.75749196511174.285662444
#Sta/Elev= 25
       0  801.16   14.05   800.4   26.56   798.6    56.6  795.39   66.61  792.12
   86.11  793.59  103.84  792.93  134.94  786.07  151.72  777.28  170.09  772.45
  191.74  770.62  200.11  764.86  206.69  763.65  216.97  764.86  224.28  768.42
  256.92  767.73  279.34   768.6  289.35  769.75  304.36  776.37  309.55  776.95
  329.39  776.53   344.4  777.39  361.92   780.9  383.69  788.55     400  792.51
#Mann= 3 , 0 , 0
       0    0.06       0  200.11   0.035       0  216.97    0.06       0
Bank Sta=200.11,216.97
XS Rating Curve= 0 ,0
Exp/Cntr=0.3,0.1
LCMann Table=0
Composite Channel Slope=5